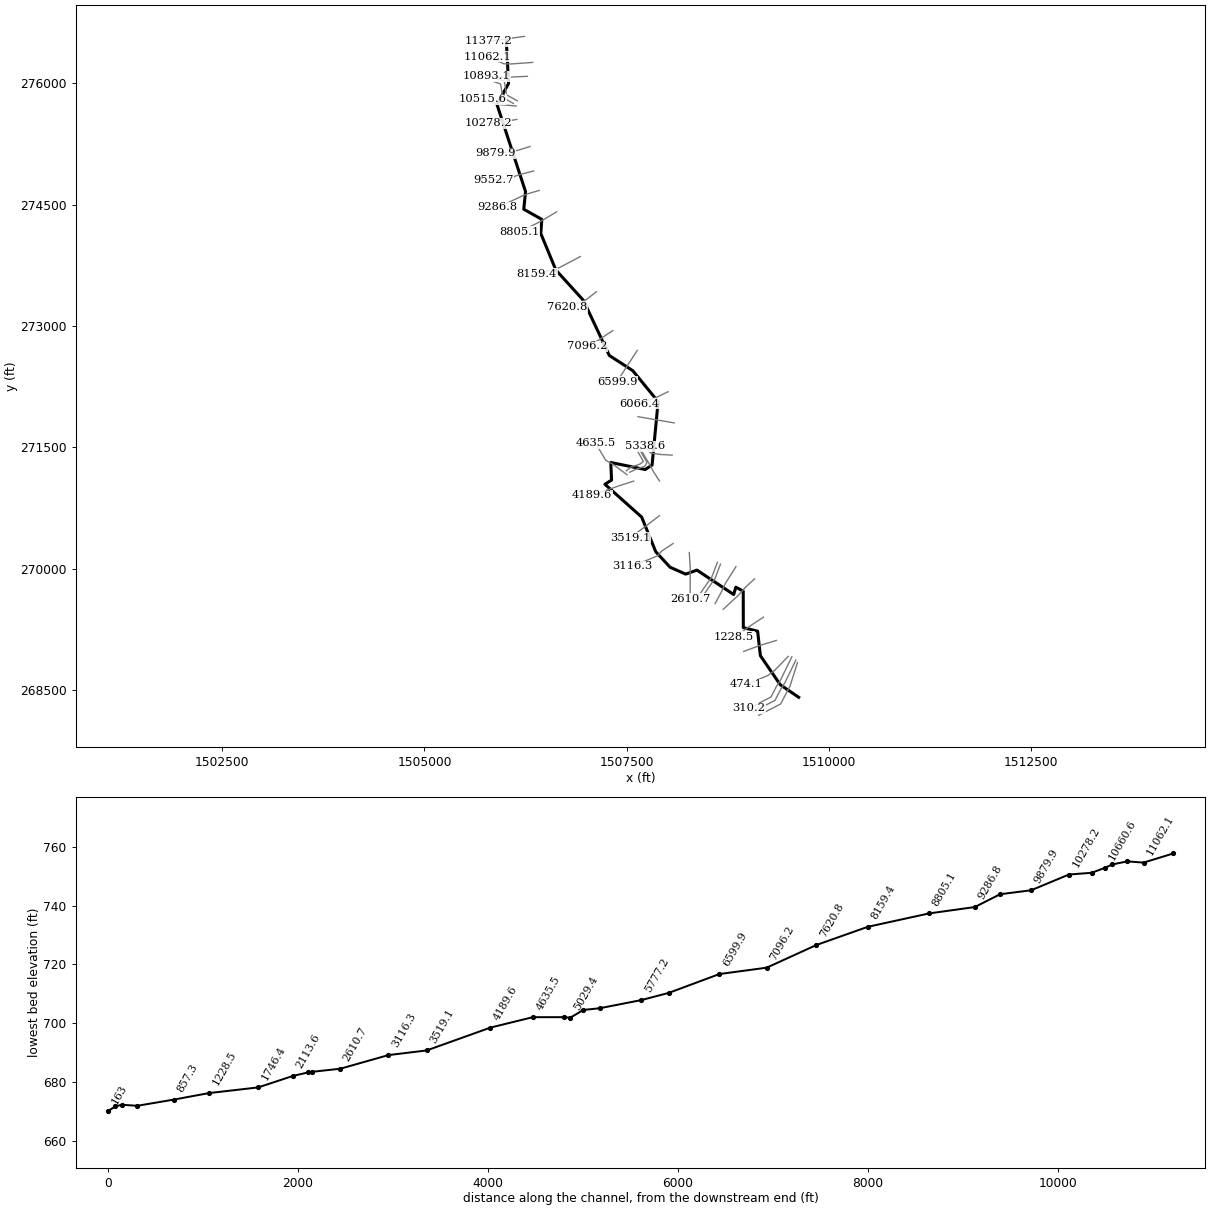
--- BRRN1.prj (project) ---

Proj Title=BRRN1
Current Plan=p01
Default Exp/Contr=0,0
English Units
Geom File=g01
Flow File=f01
Plan File=p01
BEGIN DESCRIPTION:
END DESCRIPTION:
DSS Export Rating Curves= 0
DSS Export Rating Curve Sorted= 0
DSS Export Volume Flow Curves= 0
DXF OffsetX= 0
DXF OffsetY= 0
DXF ScaleX= 0
DXF ScaleY= 0

--- BRRN1.p01 (plan) ---

Plan Title=Floodplain
Program Version=4.00
Geom File=g01
Flow File=f01
K Sum by GR=0
Std Step Tol=0.01
Critical Tol=0.01
Num of Std Step Trials=20
Max Error Tol=0.3
Flow Tol Ratio=0.001
Split Flow NTrial=30
Split Flow Tol=0.02
Split Flow Ratio=0.02
Log Output Level=0
Friction Slope Method=1
Unsteady Friction Slope Method=2
Unsteady Bridges Friction Slope Method=1
Global Log Level=0
CheckData=False
Run HTab=0
Run UNet=0
Run PostProcess=0
UNET Theta=0
UNET Theta Warmup=0
UNET ZTol=0
UNET ZSATol=0
UNET MxIter=0
UNET MaxInSteps=0
UNET DtIC=0
UNET DtMin=0
UNET MaxCRTS=0
UNET WFStab=0
UNET SFStab=0
UNET WFX=0
UNET SFX=0
UNET DSS MLevel=0
UNET DZMax Abort=0
UNET Convert EG Bridges=0
UNET Use Existing IB Tables=0
UNET Froude Limit=0
UNET Froude Power=0
Write IC File=0
Echo Input=False
Echo Output=False
Write Detailed=0

--- BRRN1.f01 (steady flow) ---

Flow Title=NFF Regression Equation
Program Version=4.10
Number of Profiles= 1
Profile Names=P100yr
River Rch & RM=BRRN1,Main            ,11377.2
907.1693
River Rch & RM=BRRN1,Main            ,11062.1
986.7498
River Rch & RM=BRRN1,Main            ,9552.7
1013.474
River Rch & RM=BRRN1,Main            ,9286.8
1090.412
River Rch & RM=BRRN1,Main            ,8159.4
1146.975
River Rch & RM=BRRN1,Main            ,4635.5
1223.369
River Rch & RM=BRRN1,Main            ,474.1
1308.763
Boundary for River Rch & Prof#=BRRN1,Main            , 1
Up Type= 0
Dn Type= 3
Dn Slope=0.005
DSS Import GetInterval= 0
DSS Import GetPeak= 0
DSS Import FillOption= 0

--- BRRN1.g01 (geometry) ---

Geom Title=USGS 10m DEM
Program Version=4.10

River Reach=BRRN1           ,Main
Reach XY= 30
     1506010.449      276559.709      1506040.31      275997.556
     1505896.907      275738.181     1506250.005      274660.904
     1506228.304      274442.588     1506451.394      274317.588
     1506438.373      274143.109     1506625.005      273691.286
     1506965.717      273316.286     1507285.596      272634.863
     1507576.438      272445.948     1507889.383      272063.801
     1507814.799      271280.286      1507730.22      271224.156
     1507304.245      271311.042     1507313.472      271093.442
       1507231.2      271041.925     1507685.623      270636.712
     1507860.165      270207.662     1508037.013      270016.204
     1508230.009      269930.856     1508369.949      269980.066
     1508823.604      269678.655     1508850.516      269769.386
     1508942.015      269719.407     1508942.827       269269.11
     1509119.873      269225.262     1509153.793      268922.465
     1509399.919      268562.582     1509627.932      268407.678

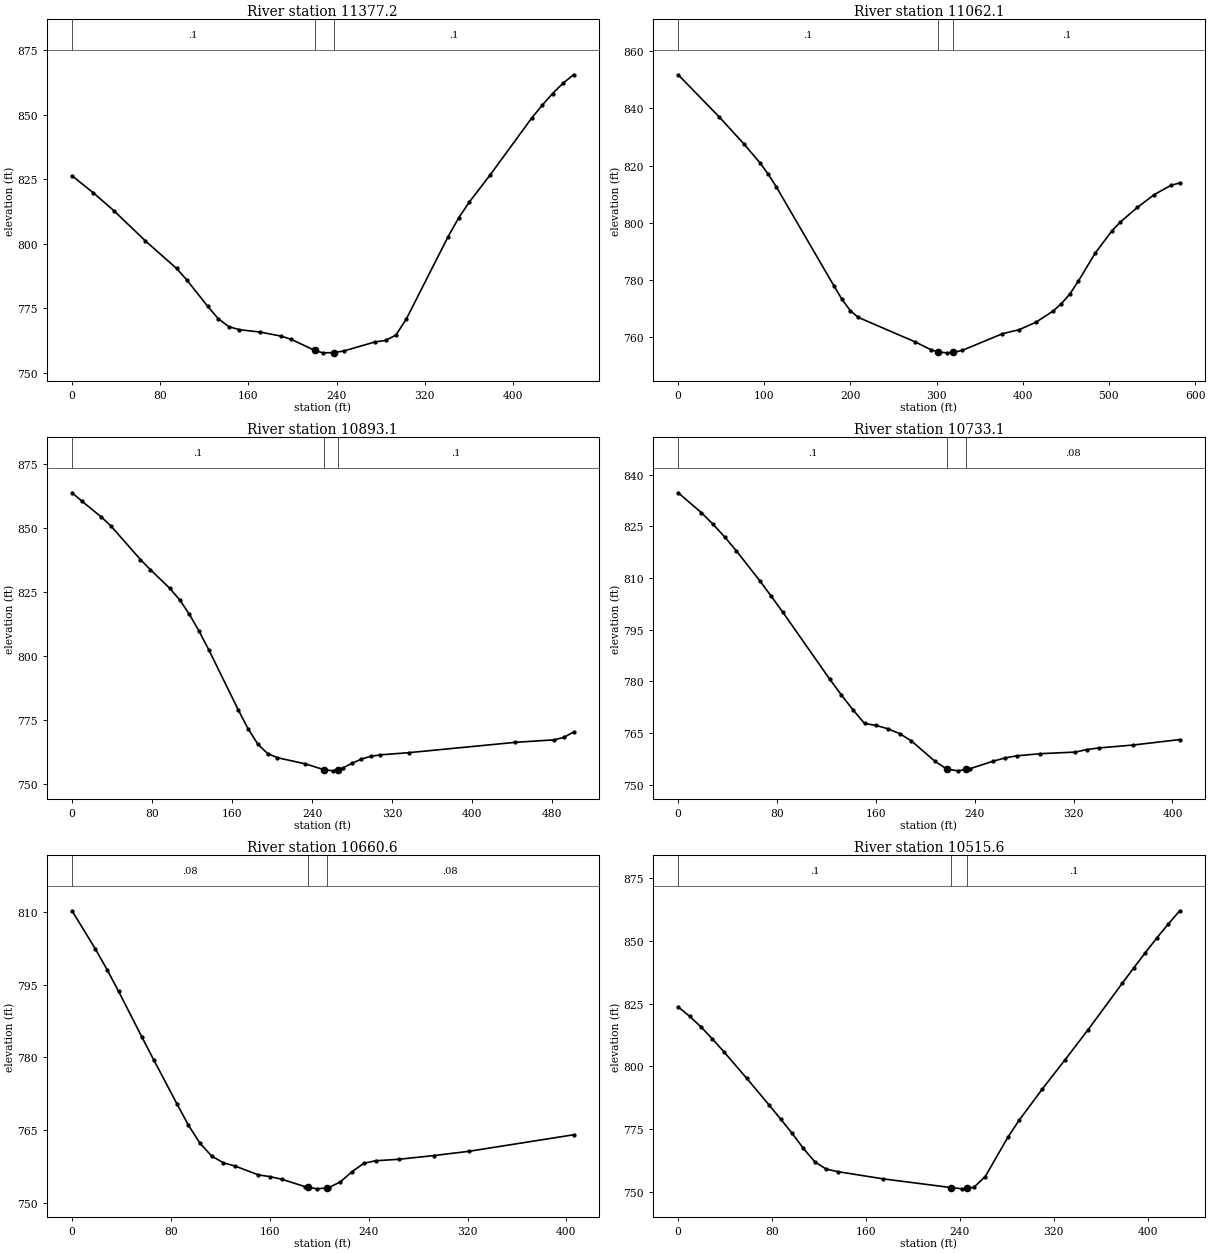
Type RM Length L Ch R = 1 ,11377.2 ,317.9,315.1,310.6
XS GIS Cut Line= 3
     1506237.275      276579.862     1506011.771      276549.797
     1505786.266      276519.732
#Sta/Elev= 30
       0   826.4      19   819.9    37.9  812.88    66.4  801.22    94.8  790.47
   104.3   785.9   123.2  775.72   132.7  770.96   142.2  767.92   151.7  766.72
   170.6   765.8   189.6  764.23   199.1  762.94     220  758.71   227.5  757.74
  237.67 757.828   246.5  758.46   274.9  761.97   284.4  762.54   293.8   764.6
   303.3  770.87   341.2  802.81   350.7  810.02   360.2  816.08   379.2  826.65
   417.1   848.8   426.6   853.8     436   858.3   445.5  862.31     455  865.57
#Mann= 3 , 0 , 0
       0      .1       0     220    .045       0  237.67      .1       0
Bank Sta=220,237.67
XS Rating Curve= 0 ,0
Exp/Cntr=0.3,0.1

Type RM Length L Ch R = 1 ,11062.1 ,167.4,169,170.5
XS GIS Cut Line= 4
      1506338.87      276258.352     1506073.245      276239.255
     1505982.967      276240.991      1505776.37      276331.269
#Sta/Elev= 30
       0  851.77    47.6  837.06    76.1  827.67    95.1  820.95   104.6  817.01
   114.1  812.51   180.7  778.06   190.2  773.28   199.7  769.38   209.2  766.98
   275.3  758.41   293.4   755.7  301.09754.9737   311.5  754.61     319  754.76
   329.5  755.44   376.2  761.27   395.8   762.7   415.4  765.33     435  769.18
   444.8  771.78   454.6  775.15   464.4  779.62     484  789.43   503.6  797.28
   513.4  800.35     533  805.42   552.7  809.92   572.3  813.18   582.1  813.95
#Mann= 3 , 0 , 0
       0      .1       0  301.09    .045       0     319      .1       0
Bank Sta=301.09,319
XS Rating Curve= 0 ,0
Exp/Cntr=0.3,0.1

Type RM Length L Ch R = 1 ,10893.1 ,198.6,160.1,121.5
XS GIS Cut Line= 4
     1506272.898      276086.477      1506067.82      276076.892
     1505965.606      276071.467     1505772.464      276085.573
#Sta/Elev= 30
       0   863.9     9.8  860.64    29.3  854.41    39.1  850.81    68.4  837.74
    78.2  833.86    97.8  826.45   107.5  822.02   117.3  816.34   127.1  809.62
   136.9  802.27   166.2  778.86     176  771.48   185.8  765.45   195.5   761.8
   205.3  760.18   233.2  757.78   251.8  755.49   261.1  755.04   265.5  755.56
   270.4  756.14   279.7  757.96     289   759.6   298.4   760.7   307.7  761.28
   336.7  762.16   443.2   766.2     482  767.18   491.6  768.14   501.3  770.24
#Mann= 3 , 0 , 0
       0      .1       0   251.8    .045       0   265.5      .1       0
Bank Sta=251.8,265.5
XS Rating Curve= 0 ,0
Exp/Cntr=0.3,0.1

Type RM Length L Ch R = 1 ,10733.1 ,73.7,72.4,74.3
XS GIS Cut Line= 4
     1506147.681       275783.49     1506015.736      275856.406
     1505987.959      276024.809     1505908.098      276051.936
#Sta/Elev= 30
       0  834.74    18.8  828.97    28.3  825.58    37.7  821.87    47.1  817.86
      66   809.2    75.4  804.65    84.8  799.98   122.5  780.67   131.9  776.09
   141.3  771.76   150.8  767.74   160.2  767.16   169.7   766.2   179.2   764.8
   188.7  762.68   207.6  756.81   217.5  754.47   226.6  753.98   232.5  754.37
   236.1   754.6   255.1  756.81   264.5  757.73     274  758.34     293  758.96
   321.4  759.43   330.8  760.16   340.2  760.62   368.3  761.48   405.8  763.06
#Mann= 3 , 0 , 0
       0      .1       0   217.5    .045       0   232.5     .08       0
Bank Sta=217.5,232.5
XS Rating Curve= 0 ,0
Exp/Cntr=0.3,0.1

Type RM Length L Ch R = 1 ,10660.6 ,112.5,145.1,175.7
XS GIS Cut Line= 4
     1506101.023      275750.938     1505969.079      275823.854
     1505941.301      275992.257      1505861.44      276019.384
#Sta/Elev= 28
       0  810.24    18.8  802.39    28.3  798.12    37.7  793.61    56.5   784.2
      66  779.54    84.8  770.45    94.2  766.01   103.6  762.26   113.1  759.62
   122.5  758.26   131.9  757.59   150.8  755.77   160.2   755.4   169.7  754.87
   188.7  753.33     191  753.22   198.2  752.89     206  753.07   207.6  753.11
   217.1  754.33   226.6  756.43   236.1  758.16   245.6  758.68   264.5  758.99
     293  759.76   321.4  760.64   405.8  764.04
#Mann= 3 , 0 , 0
       0     .08       0     191    .045       0     206     .08       0
Bank Sta=191,206
XS Rating Curve= 0 ,0
Exp/Cntr=0.3,0.1

Type RM Length L Ch R = 1 ,10515.6 ,228.3,237.3,243.5
XS GIS Cut Line= 4
     1506134.443      275719.398     1505931.535      275736.759
     1505865.346       275749.78     1505717.776      275800.778
#Sta/Elev= 30
       0  823.74     9.7     820    19.4  815.75    29.1  810.98    38.8  805.89
    58.2  795.35    77.6  784.49    87.3  778.98      97  773.33   106.7  767.26
   116.4  761.92   126.1  759.03   135.8  758.02   174.6  755.13   232.6  751.65
   242.2  751.15   246.4  751.41   251.8  751.74   261.5  755.99   280.9  771.77
   290.6  778.61   310.1  790.91   329.7  802.71   349.2  814.63   378.4   833.2
   388.2  839.35     398  845.36   407.7   851.2   417.5  856.77   427.2  862.06
#Mann= 3 , 0 , 0
       0      .1       0   232.6    .045       0   246.4      .1       0
Bank Sta=232.6,246.4
XS Rating Curve= 0 ,0
Exp/Cntr=0.3,0.1

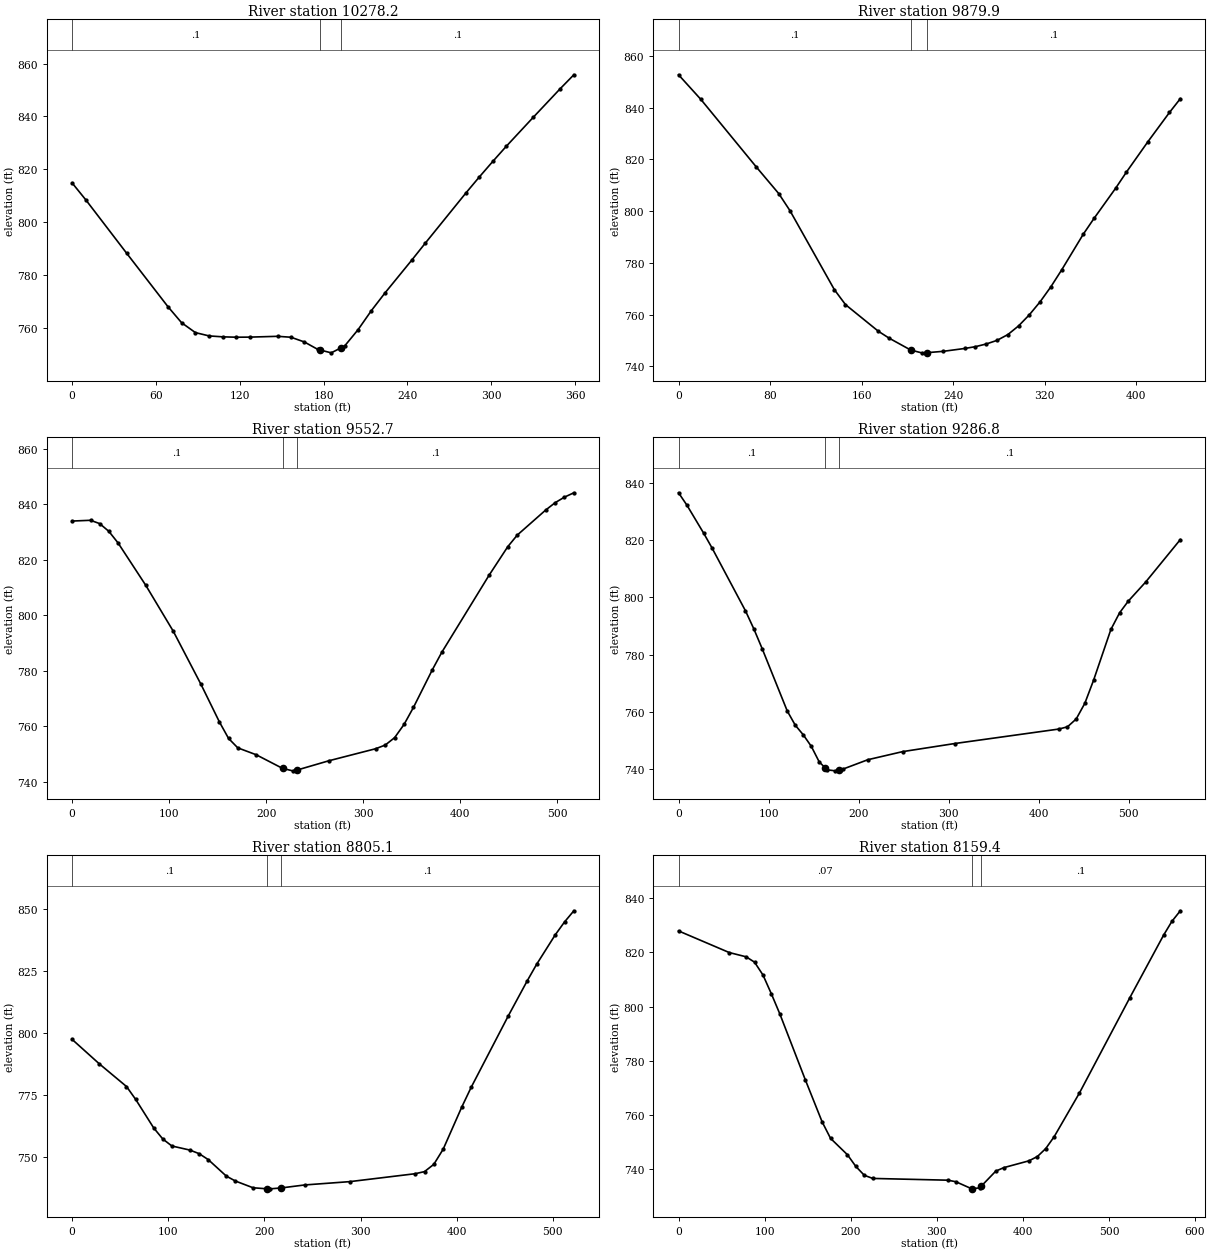
Type RM Length L Ch R = 1 ,10278.2 ,396.5,398.3,397.6
XS GIS Cut Line= 4
     1506142.473      275554.034     1505997.941       275526.69
     1505912.004      275517.575     1505787.004      275504.554
#Sta/Elev= 30
       0  814.86     9.8  808.46    39.2  788.16    68.6  768.05    78.4  761.96
    88.3  758.22    98.1  756.97   107.9  756.62   117.7  756.48   127.5  756.52
   147.1  756.82   156.7  756.47   166.3  754.68   175.9  751.87   177.6  751.64
   185.5  750.57   192.6  752.48   195.1  753.15   204.7  759.31   214.3  766.57
   223.9  773.16   243.2  785.66   252.8  792.03   281.8  810.96   291.5  817.08
   301.2  822.99   310.8  828.68   330.2   839.7   349.5  850.52   359.2  855.75
#Mann= 3 , 0 , 0
       0      .1       0   177.6    .045       0   192.6      .1       0
Bank Sta=177.6,192.6
XS Rating Curve= 0 ,0
Exp/Cntr=0.3,0.1

Type RM Length L Ch R = 1 ,9879.9  ,322.2,327.2,333
XS GIS Cut Line= 4
     1506304.799       275218.53     1506156.361      275171.655
     1506082.143      275157.332     1505876.414      275132.593
#Sta/Elev= 30
       0  852.67    19.5  843.16    68.1  816.97    87.6  806.74    97.3  800.22
   136.2  769.62   145.9  763.85   174.6  753.57     184   750.9   202.9   746.3
   212.4  745.22   216.7  745.27   231.2   745.8   250.1  746.91   259.5  747.61
   268.9  748.64   278.3  750.04   287.8  752.28   297.2  755.65   306.6  759.94
     316  764.96   325.4  770.76   334.9  777.33   353.7  791.07   363.1  797.18
     382  808.85   391.4  815.06   410.2  826.83     429   838.1   438.5  843.44
#Mann= 3 , 0 , 0
       0      .1       0   202.9    .045       0   216.7      .1       0
Bank Sta=202.9,216.7
XS Rating Curve= 0 ,0
Exp/Cntr=0.3,0.1

Type RM Length L Ch R = 1 ,9552.7  ,267,265.9,264.5
XS GIS Cut Line= 4
     1506351.023      274916.338     1506158.315      274865.991
      1506088.87      274838.213     1505849.287      274798.283
#Sta/Elev= 30
       0  833.94      19  834.22    28.4  833.03    37.9  830.23    47.4  826.04
    75.9  810.78   104.3  794.18   132.8  775.05   151.8  761.48   161.2  755.55
   170.7  752.15   189.7  749.66   216.8  744.75   227.2  743.86   231.8  744.15
   264.6   747.5   312.8  751.84   322.6  753.16   332.3  755.84     342  760.61
   351.7  766.76   371.1   780.3   380.8  786.58   429.4  814.31   448.8  824.69
   458.6  828.88   487.7  837.86   497.4  840.51   507.1  842.55   516.9  844.14
#Mann= 3 , 0 , 0
       0      .1       0   216.8    .045       0   231.8      .1       0
Bank Sta=216.8,231.8
XS Rating Curve= 0 ,0
Exp/Cntr=0.3,0.1

Type RM Length L Ch R = 1 ,9286.8  ,475.4,481.7,486.2
XS GIS Cut Line= 4
     1506419.165      274675.344      1506303.28       274641.49
     1506227.759      274615.449     1505904.842      274464.407
#Sta/Elev= 30
       0  836.47     9.3  832.15    27.9  822.38    37.2  817.22    74.3  795.32
    83.6  789.01    92.9  782.08   120.7  760.38   129.6  755.42   138.5  752.06
   147.4  748.05   156.2  742.62     163  740.51   165.1  739.86     174  739.51
     178   739.8   182.9  740.16   210.2  743.39   248.8  746.21   306.6  749.03
   422.2  754.08   431.8  754.86   441.5  757.59   451.1  763.07   460.8  771.12
     480   788.8   489.7  794.63   499.3  798.68   518.6  805.34   557.1  820.15
#Mann= 3 , 0 , 0
       0      .1       0     163    .045       0     178      .1       0
Bank Sta=163,178
XS Rating Curve= 0 ,0
Exp/Cntr=0.3,0.1

Type RM Length L Ch R = 1 ,8805.1  ,649.8,645.7,639.7
XS GIS Cut Line= 4
      1506634.66      274410.804     1506481.014      274318.357
     1506410.702      274279.294     1506176.327      274162.107
#Sta/Elev= 30
       0  797.42    28.3  787.59    56.6  778.47    66.1  773.31    84.9  761.81
    94.4  757.35   103.8  754.56   122.7   752.9   132.1  751.48   141.6  749.09
   160.4  742.46   169.9  740.47   188.2  737.77   202.4  737.36   206.1  737.34
   217.4   737.7   241.9   738.9   288.9  740.24   356.8  743.42   366.5  744.26
   376.2   747.2   385.9  753.27   405.3  770.26     415  778.13   453.8  806.99
   473.3  820.94     483  827.53   502.4  839.41   512.1  844.61   521.8   849.1
#Mann= 3 , 0 , 0
       0      .1       0   202.4    .045       0   217.4      .1       0
Bank Sta=202.4,217.4
XS Rating Curve= 0 ,0
Exp/Cntr=0.3,0.1

Type RM Length L Ch R = 1 ,8159.4  ,533.4,538.6,541.7
XS GIS Cut Line= 4
     1506927.412      273857.311     1506666.995      273720.158
     1506587.134      273695.852     1506389.217      273642.033
#Sta/Elev= 30
       0  827.94    58.9  819.96    78.5  818.39    88.3  816.41    98.1  811.67
   107.9  804.68   117.7   797.3   147.2  773.07   166.8  757.49   176.6   751.4
   196.2  745.36     206  741.03   215.8  737.78   225.6  736.62   312.9  735.97
   322.2   735.4   340.7  732.78     350  733.17   351.7  733.78   368.5  739.31
   377.8   740.6   407.1  743.12   416.9  744.71   426.6  747.65   436.4  752.04
   465.7  768.14   524.3  803.33   563.4  826.34   573.1  831.46   582.9  835.37
#Mann= 3 , 0 , 0
       0     .07       0   340.7    .045       0   351.7      .1       0
Bank Sta=340.7,351.7
XS Rating Curve= 0 ,0
Exp/Cntr=0.3,0.1

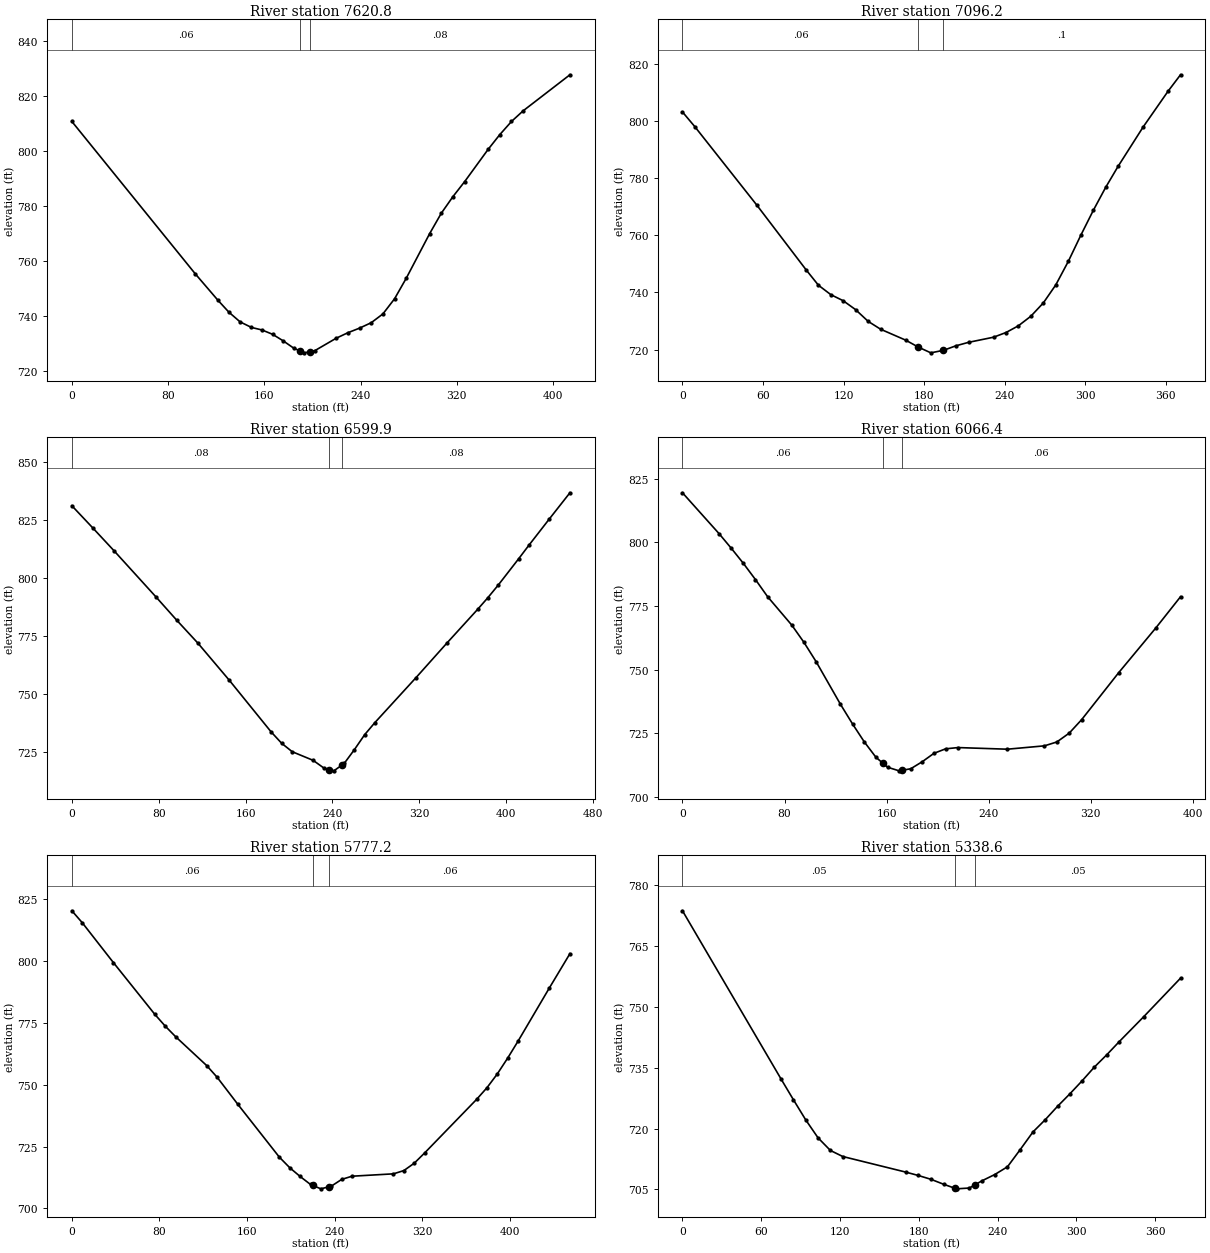
Type RM Length L Ch R = 1 ,7620.8  ,521.1,524.6,527.5
XS GIS Cut Line= 4
     1507125.546      273422.523     1507008.358      273330.075
     1506945.858      273297.523     1506762.264      273233.721
#Sta/Elev= 30
       0  810.75   102.6  755.35   121.3  745.81   130.6  741.38   139.9  737.87
   149.3  735.86   158.1  734.93   166.9  733.36   175.7  730.98   184.5  728.31
   189.3727.3857   193.3  726.62   197.7727.0325   202.1  727.44   219.7  731.92
   229.4  733.92   239.2  735.61   248.9  737.58   258.6  740.77   268.3  746.28
     278  753.74   297.5     770   307.2  777.42   316.9  783.47   326.6   788.9
   346.1  800.62   355.8  805.98   365.5  810.75   375.2  814.63   414.1  827.74
#Mann= 3 , 0 , 0
       0     .06       0   189.3    .045       0   197.7     .08       0
Bank Sta=189.3,197.7
XS Rating Curve= 0 ,0
Exp/Cntr=0.3,0.1

Type RM Length L Ch R = 1 ,7096.2  ,487.2,496.3,504.7
XS GIS Cut Line= 4
     1507329.973      272942.054       1507221.9      272871.742
     1507152.889      272823.565     1507013.566      272749.346
#Sta/Elev= 30
       0  803.08     9.2  797.95    55.3  770.58    92.1  747.91   101.3  742.52
   110.5  739.24   119.7  737.12   128.9  734.02   138.3  729.91   147.6  727.15
   166.3  723.33   175.7   720.9     185   718.9   194.4  719.78   203.7  721.36
   213.1  722.57   231.7  724.36     241     726   250.2  728.34   259.5  731.69
   268.8  736.34   278.1  742.65   287.4  750.85   296.7  759.96     306  768.66
   315.2  776.69   324.5  784.08   343.1  797.79   361.7  810.32     371  816.08
#Mann= 3 , 0 , 0
       0     .06       0   175.7    .045       0   194.4      .1       0
Bank Sta=175.7,194.4
XS Rating Curve= 0 ,0
Exp/Cntr=0.3,0.1

Type RM Length L Ch R = 1 ,6599.9  ,546.1,533.5,519.9
XS GIS Cut Line= 3
      1507631.31       272696.01     1507504.528      272501.765
     1507381.586      272311.055
#Sta/Elev= 28
       0  831.01    19.3  821.43    38.7  811.68    77.3  791.81    96.6  781.68
     116  771.85     145  755.82   183.6  733.53   193.3  728.62     203     725
   222.3  721.27     232  718.02  237.19717.3189   241.4  716.75     249  719.29
   250.9  719.93   260.3  725.88   269.8  732.35   279.2  737.55     317  756.88
   345.4  771.74   373.8  786.32   383.2  791.33   392.7  796.73   411.6  808.12
     421  813.92     440  825.36   458.9   836.6
#Mann= 3 , 0 , 0
       0     .08       0  237.19    .045       0     249     .08       0
Bank Sta=237.19,249
XS Rating Curve= 0 ,0
Exp/Cntr=0.3,0.1

Type RM Length L Ch R = 1 ,6066.4  ,302.5,289.2,275.4
XS GIS Cut Line= 4
     1508012.264      272186.087     1507892.473      272127.493
     1507826.066      272097.545     1507651.587      272038.951
#Sta/Elev= 30
       0  819.43    28.6  803.44    38.1  797.75    47.6  791.82    57.2  785.38
    66.7  778.67    85.7  767.49    95.2  760.75   104.8  753.12   123.8  736.46
   133.4  728.64   142.5  721.69   151.6  715.67   156.9  713.39   160.7  711.76
   169.8  710.34   171.9  710.53   178.9  711.16     188  713.95   197.1  717.22
   206.2  718.97   215.9  719.47   254.6  718.83   283.7  720.15   293.4  721.67
   303.1  725.14   312.8  730.41   341.8  748.82   370.9  766.37   390.3  778.64
#Mann= 3 , 0 , 0
       0     .06       0   156.9    .045       0   171.9     .06       0
Bank Sta=156.9,171.9
XS Rating Curve= 0 ,0
Exp/Cntr=0.3,0.1

Type RM Length L Ch R = 1 ,5777.2  ,436.9,438.6,438.7
XS GIS Cut Line= 3
     1508088.383      271800.661     1507864.154      271839.101
     1507639.925      271877.541
#Sta/Elev= 30
       0  820.38     9.5  815.54    37.9  799.44    75.8  778.47    85.3  773.71
    94.8  769.43   123.2  757.74   132.7  753.03   151.7  742.03   189.6  720.68
   199.1  716.41   208.5   712.9     218  709.66     220  709.29   227.5  707.89
     235  708.75     237  708.98   246.5  711.71   255.9     713   293.8  713.96
   303.3  715.28   312.8  718.27   322.3  722.42   369.7  744.06   379.2  748.79
   388.6  754.34   398.1  760.76   407.6  767.63     436     789     455  803.03
#Mann= 3 , 0 , 0
       0     .06       0     220    .045       0     235     .06       0
Bank Sta=220,235
XS Rating Curve= 0 ,0
Exp/Cntr=0.3,0.1

Type RM Length L Ch R = 1 ,5338.6  ,192.5,170.5,148.5
XS GIS Cut Line= 4
     1508063.046      271402.232     1507922.421      271410.045
     1507797.421      271426.972       1507721.9      271510.305
#Sta/Elev= 29
       0  773.75    75.1  732.23    84.5  727.12    93.9  722.14   103.3   717.7
   112.7  714.59   122.1   713.1     170  709.26   179.6  708.42   189.4  707.46
   199.1  706.23   207.9  705.22   208.8  705.12   218.5  705.32   222.9  706.13
   228.2  707.11   237.9  708.65   247.6  710.57   257.3  714.81     267  719.16
   276.4   722.2   285.7  725.48   295.1  728.56   304.5   731.8   313.8  735.18
   323.2   738.2   332.6  741.41   351.3  747.58   379.4  757.11
#Mann= 3 , 0 , 0
       0     .05       0   207.9    .045       0   222.9     .05       0
Bank Sta=207.9,222.9
XS Rating Curve= 0 ,0
Exp/Cntr=0.3,0.1

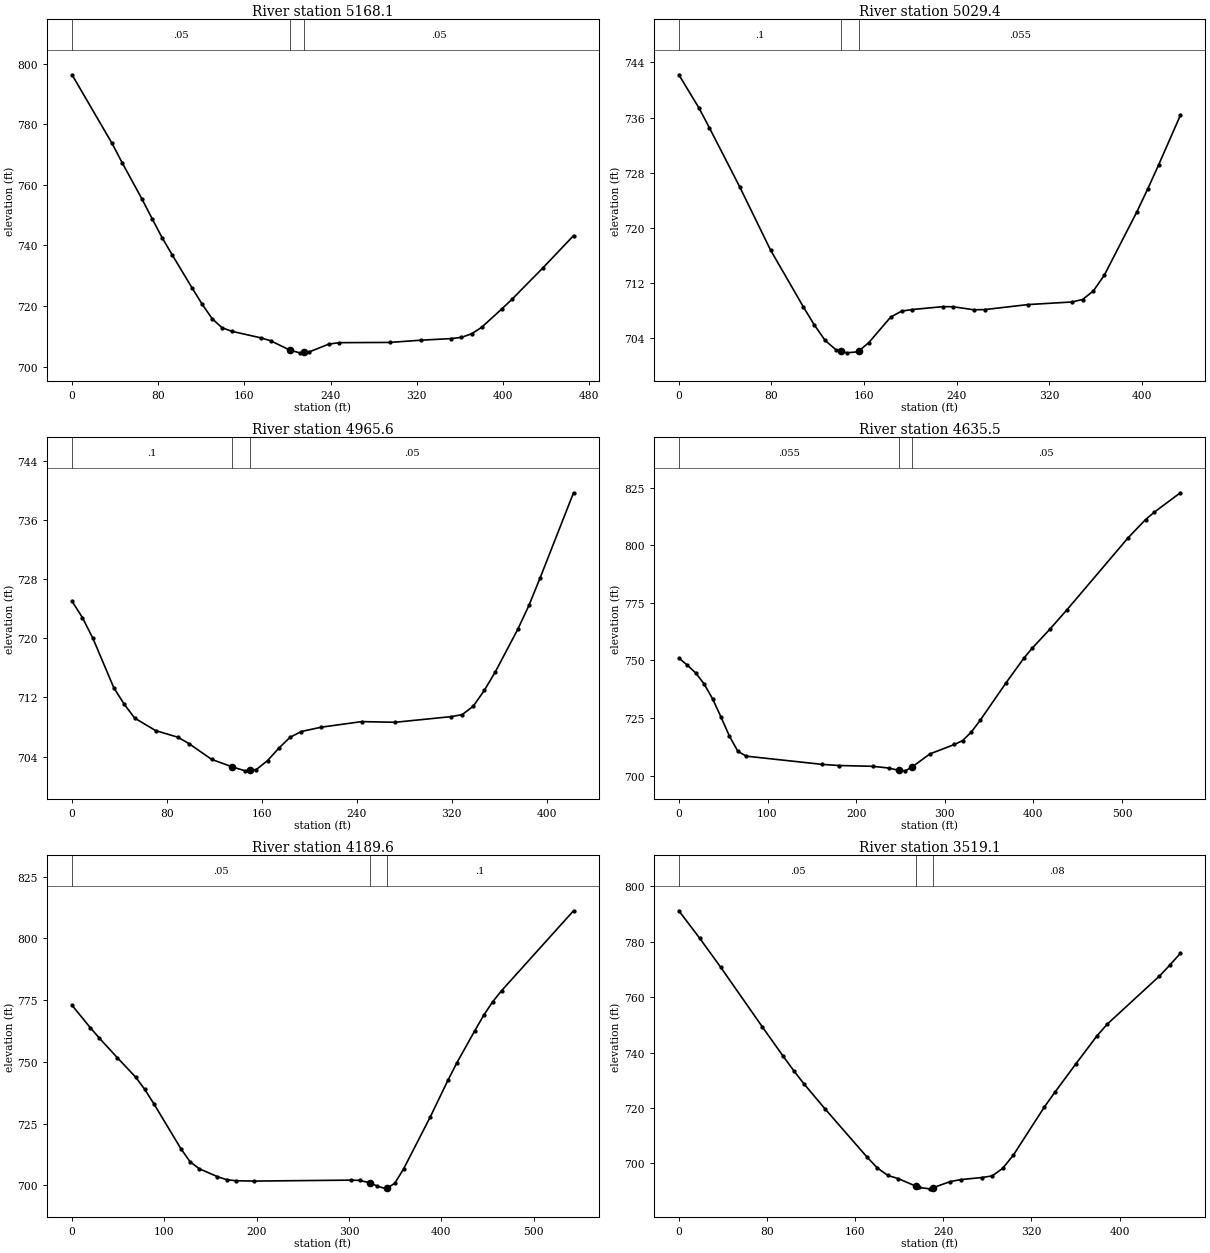
Type RM Length L Ch R = 1 ,5168.1  ,182.5,138.8,94.5
XS GIS Cut Line= 4
     1507906.796       271081.92     1507831.275      271199.107
       1507784.4      271286.347     1507668.514      271481.659
#Sta/Elev= 30
       0  796.39    37.2  773.69    46.5  767.36    65.1  755.23    74.4  748.81
    83.6   742.6    92.9  736.95   111.5  725.95   120.8  720.61   130.1  715.81
   139.4   712.8   148.4  711.65   175.4  709.48   184.4  708.52   202.4  705.41
   211.4  704.54   214.9  704.67   220.4  704.88   238.4  707.42   247.9   707.9
   295.2  707.98   323.6  708.71     352  709.25   361.5  709.65   370.9  710.82
   380.4  712.99   399.3  719.14   408.8  722.35   437.2  732.61   465.6  743.25
#Mann= 3 , 0 , 0
       0     .05       0   202.4    .045       0   214.9     .05       0
Bank Sta=202.4,214.9
XS Rating Curve= 0 ,0
Exp/Cntr=0.3,0.1

Type RM Length L Ch R = 1 ,5029.4  ,82.9,63.8,64.7
XS GIS Cut Line= 5
     1507539.608      271191.295     1507611.223      271225.149
     1507727.108      271265.514     1507751.848      271312.389
     1507663.306      271467.337
#Sta/Elev= 30
       0  742.21    17.6  737.33    26.4  734.52    52.8  725.89    79.2  716.81
   107.5  708.59     117  705.96   126.4   703.7   135.8  702.34   140.5  702.12
   145.3   701.9   154.7  702.05   155.5  702.16   164.2  703.39     183  707.07
   192.5  707.95   201.9  708.18   228.4   708.6   237.3  708.58   254.9  708.14
   264.3  708.17   301.9   708.9   339.5  709.27   348.9  709.63   358.2  710.87
   367.6  713.13   395.8  722.33   405.2  725.66   414.6  729.14   433.4  736.32
#Mann= 3 , 0 , 0
       0      .1       0   140.5    .045       0   155.5    .055       0
Bank Sta=140.5,155.5
XS Rating Curve= 0 ,0
Exp/Cntr=0.3,0.1

Type RM Length L Ch R = 1 ,4965.6  ,250.2,330.2,388
XS GIS Cut Line= 5
     1507496.639      271208.222     1507551.327      271252.493
     1507667.212      271292.857     1507707.577      271324.107
     1507619.035      271479.055
#Sta/Elev= 30
       0     725     8.8  722.77    17.6  719.98    35.2  713.31      44  711.08
    52.8  709.21    70.4  707.53    89.2  706.63    98.7  705.75   117.6  703.64
   134.7  702.64   145.9  702.09   149.7  702.16   155.3  702.27   164.8  703.48
   174.2  705.14   183.6  706.61   193.1   707.4   210.1  707.99   244.1  708.74
   272.3  708.65   319.3  709.41   328.7  709.68     338   710.8   347.4  712.95
   356.8  715.49   375.6   721.2     385  724.43   394.4  728.13   422.6  739.65
#Mann= 3 , 0 , 0
       0      .1       0   134.7    .045       0   149.7     .05       0
Bank Sta=134.7,149.7
XS Rating Curve= 0 ,0
Exp/Cntr=0.3,0.1

Type RM Length L Ch R = 1 ,4635.5  ,414.1,445.9,464.7
XS GIS Cut Line= 4
     1507504.452      271160.045     1507336.483      271285.045
     1507240.129      271339.732     1507116.431      271551.972
#Sta/Elev= 30
       0  751.02     9.5  747.99      19  744.56    28.6  739.74    38.1   733.3
    47.6  725.39    57.1   717.1    66.6  710.54    76.1  708.45   161.8  704.88
   180.8  704.39   218.6  704.05   237.1  703.28     248  702.28   255.5  702.08
     263  703.71   283.2  709.42   310.9  713.52   320.2  715.22     330  718.95
   339.8  723.93   369.3  740.38     389  750.85   398.8  755.38   418.4  763.47
   438.1  772.09   506.9  803.24   526.5  811.12   536.4  814.35   565.8  822.77
#Mann= 3 , 0 , 0
       0    .055       0     248    .045       0     263     .05       0
Bank Sta=248,263
XS Rating Curve= 0 ,0
Exp/Cntr=0.3,0.1

Type RM Length L Ch R = 1 ,4189.6  ,663.4,670.5,677.7
XS GIS Cut Line= 4
     1507586.483      271080.618     1507398.983      271020.722
     1507210.181      270953.014      1507072.16      270906.139
#Sta/Elev= 30
       0  772.88    19.7  763.86    29.5  759.63    49.2   751.6    68.9  743.79
    78.7  738.86    88.6  733.02   118.1  714.68   127.9  709.49   137.8  706.68
   157.5  703.48   167.3  702.28   177.2  701.83   196.8  701.68   301.9  702.07
   311.4  701.96   322.4  700.99   330.6  699.66   340.1  698.54  340.71698.6844
   349.6  700.79   359.2  706.68   387.9  727.58   407.1  742.49   416.8  749.58
   436.3  762.63     446  768.92   455.7  774.36   465.4  778.87   543.2  811.18
#Mann= 3 , 0 , 0
       0     .05       0   322.4    .045       0  340.71      .1       0
Bank Sta=322.4,340.71
XS Rating Curve= 0 ,0
Exp/Cntr=0.3,0.1

Type RM Length L Ch R = 1 ,3519.1  ,400.2,402.7,404.7
XS GIS Cut Line= 3
     1507905.823      270653.794     1507725.414      270515.219
     1507541.458      270381.239
#Sta/Elev= 30
       0  791.17      19   781.2    37.9  770.82    75.8  749.22    94.8  738.58
   104.3  733.42   113.7   728.6   132.7  719.63   170.6  702.32   180.1  698.33
   189.6  695.62     199  694.49   215.5  691.68     218  691.28   227.5  690.78
   230.5  691.17   246.4  693.41   255.9  694.12   274.9  694.86   284.4  695.45
   293.9   698.2   303.4  702.86   331.8  720.39   341.3  725.68   360.2  735.86
   379.2  745.88   388.7  750.22   436.1  767.58   445.6  771.57   455.1   775.8
#Mann= 3 , 0 , 0
       0     .05       0   215.5    .045       0   230.5     .08       0
Bank Sta=215.5,230.5
XS Rating Curve= 0 ,0
Exp/Cntr=0.3,0.1

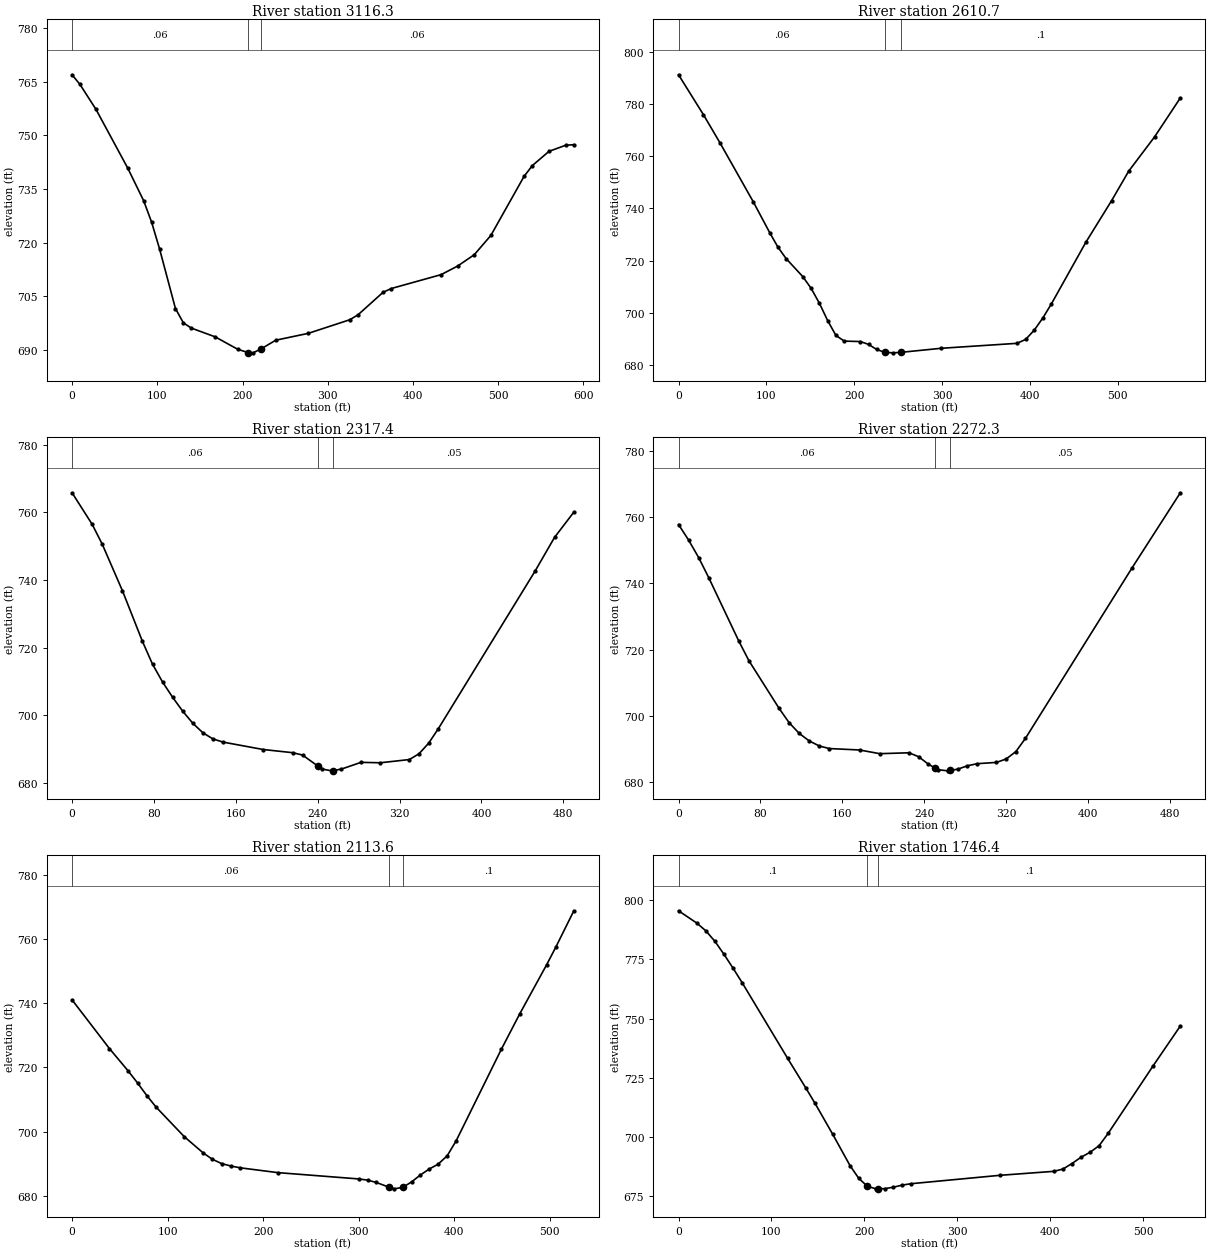
Type RM Length L Ch R = 1 ,3116.3  ,488.2,505.7,519.3
XS GIS Cut Line= 4
     1508075.094       270309.61     1507935.224      270216.686
     1507882.056      270157.007     1507567.386      270025.713
#Sta/Elev= 30
       0   766.9     9.3  764.19      28  757.26    65.3  740.83      84  731.71
    93.3  725.73   102.6   718.3   121.3  701.58   130.6  697.58   139.9  696.12
   167.9  693.67   194.6  690.17   206.4  689.29   212.3   689.2   221.4  690.25
     239  692.73   277.1  694.64   325.8  698.44   335.5  699.82   364.8  706.09
   374.5  707.17     433  711.05   452.4  713.45   471.9  716.61   491.4     722
   530.4  738.52   540.1  741.53   559.6   745.5   579.1   747.2   588.8  747.37
#Mann= 3 , 0 , 0
       0     .06       0   206.4    .045       0   221.4     .06       0
Bank Sta=206.4,221.4
XS Rating Curve= 0 ,0
Exp/Cntr=0.3,0.1

Type RM Length L Ch R = 1 ,2610.7  ,306.3,293.3,281
XS GIS Cut Line= 4
      1508274.93      270197.532     1508286.353       270009.22
     1508286.353      269871.199     1508284.148      269626.554
#Sta/Elev= 30
       0  791.32    28.3  776.03    47.2  765.18    84.9  742.67   103.8  730.71
   113.2  725.13   122.6  720.71   141.5  713.82   150.9  709.36   160.4  703.59
   169.8  696.94   179.2  691.24   188.7  689.08   207.1   688.9   216.3  687.82
   225.5  685.88   234.7  684.77   243.9  684.57   253.1  684.76   299.1  686.32
   385.4  688.22   395.2  689.73     405  693.28   414.8  697.97   424.5  703.36
   463.7     727     493  742.97   512.6  754.36     542  767.49   571.3  782.43
#Mann= 3 , 0 , 0
       0     .06       0   234.7    .045       0   253.1      .1       0
Bank Sta=234.7,253.1
XS Rating Curve= 0 ,0
Exp/Cntr=0.3,0.1

Type RM Length L Ch R = 1 ,2317.4  ,44.7,45.1,44.8
XS GIS Cut Line= 4
     1508622.724      270076.929     1508552.412      269893.335
     1508501.631      269824.324     1508384.443      269652.449
#Sta/Elev= 30
       0  765.82    19.7  756.45    29.5  750.59    49.2  736.84    68.8  721.81
    78.6   715.1    88.5  709.77    98.3  705.28   108.1  701.18     118   697.6
   127.8   694.8   137.6  692.98   147.4  692.04   186.8  689.84   215.6   688.9
   225.2   688.2   240.4  684.89   244.2  684.07   253.7  683.53   255.4  683.62
   263.2  684.05   282.3  686.04   301.2  685.92   329.6  686.87     339  688.58
   348.5  691.74   357.9  696.01   452.5  742.69   471.4  752.61   490.3   760.1
#Mann= 3 , 0 , 0
       0     .06       0   240.4    .045       0   255.4     .05       0
Bank Sta=240.4,255.4
XS Rating Curve= 0 ,0
Exp/Cntr=0.3,0.1

Type RM Length L Ch R = 1 ,2272.3  ,154.4,158.7,162.9
XS GIS Cut Line= 4
     1508660.485      270053.491     1508590.172      269869.897
     1508539.391      269800.887     1508422.204      269629.012
#Sta/Elev= 30
       0  757.82     9.8  753.13    19.7   747.8    29.5  741.75      59  722.49
    68.8  716.61    98.3  702.18   108.1  697.86     118  694.61   127.8  692.34
   137.6  690.82   147.4  690.05   176.9  689.62   196.6   688.5   225.2  688.77
   234.7  687.57   244.2   685.3   250.3  684.24   253.7  683.65   263.2  683.31
   265.3  683.42   272.8  683.81   282.3  684.84   291.7  685.47   310.6  685.86
   320.1  686.89   329.6  689.13     339  693.15     443  744.64   490.3  767.42
#Mann= 3 , 0 , 0
       0     .06       0   250.3    .045       0   265.3     .05       0
Bank Sta=250.3,265.3
XS Rating Curve= 0 ,0
Exp/Cntr=0.3,0.1

Type RM Length L Ch R = 1 ,2113.6  ,359.9,367.2,361.2
XS GIS Cut Line= 4
     1508851.891      270023.543     1508721.683      269816.512
     1508661.787      269691.512     1508594.079      269566.512
#Sta/Elev= 30
       0  741.04    39.1  725.87    58.7   718.9    68.5  715.16    78.3  711.19
      88   707.6   117.4  698.42     137   693.4   146.7  691.38   156.5  690.02
   166.3  689.25   176.1  688.69   215.2   687.2     300  685.23   309.3  684.86
   318.5  684.13  332.24682.6033     337  682.14   346.2  682.59   355.5  684.32
   364.7  686.47   373.9  688.32   383.2  689.82   392.7  692.44   402.1  697.12
   449.5  725.71   468.5   736.6   496.9  752.04   506.4  757.48   525.3  768.81
#Mann= 3 , 0 , 0
       0     .06       0  332.24    .045       0   346.2      .1       0
Bank Sta=332.24,346.2
XS Rating Curve= 0 ,0
Exp/Cntr=0.3,0.1

Type RM Length L Ch R = 1 ,1746.4  ,521.1,517.8,513.1
XS GIS Cut Line= 4
      1509082.36      269872.501     1508967.776      269765.731
     1508880.537      269668.074      1508695.23       269496.29
#Sta/Elev= 30
       0  795.47    19.6   790.3    29.4  787.02    39.2  782.58    48.9  777.13
    58.7  771.26    68.5  765.14   117.5   733.2     137  720.77   146.8  714.37
     166  701.22   184.7  687.96     194  682.66   203.4  679.26   212.7  678.22
   215.2  678.24   222.1   678.3   231.4  678.92   240.8   679.8   250.2  680.38
   345.9  683.92   404.2  685.61   413.9  686.58   423.6   688.9   433.4  691.57
   443.1  693.64   452.8  696.43   462.5  701.61   511.1   730.2   540.2  746.88
#Mann= 3 , 0 , 0
       0      .1       0   203.4    .045       0   215.2      .1       0
Bank Sta=203.4,215.2
XS Rating Curve= 0 ,0
Exp/Cntr=0.3,0.1

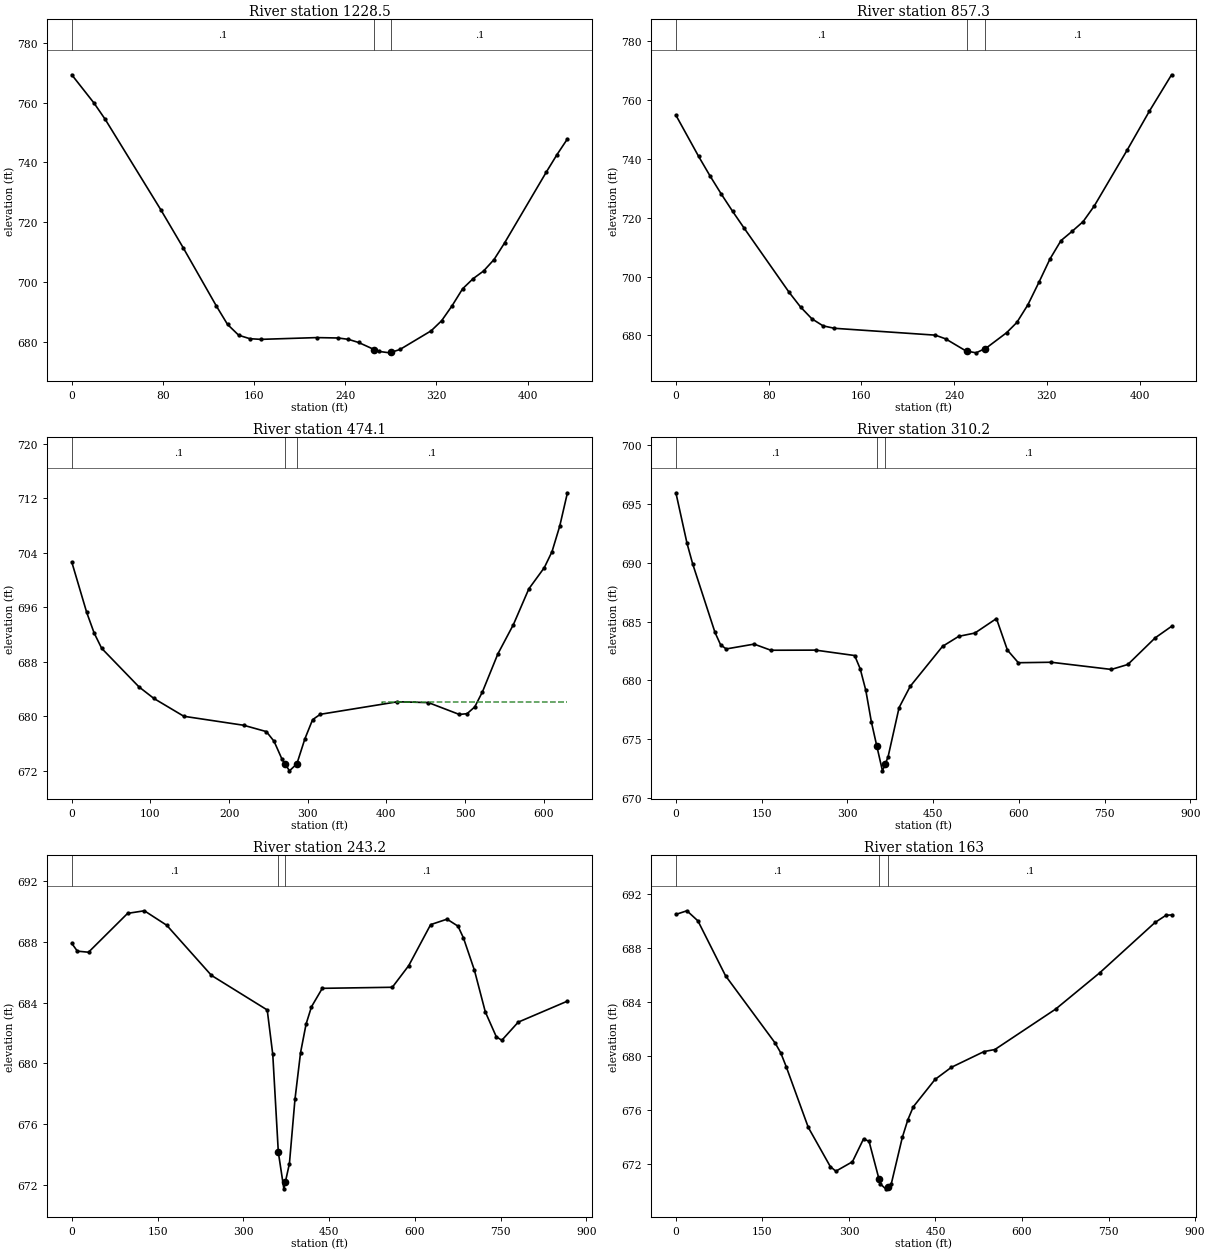
Type RM Length L Ch R = 1 ,1228.5  ,376.4,371.3,362.7
XS GIS Cut Line= 4
     1509191.735      269398.543     1509004.235      269274.845
     1508946.943      269230.574     1508829.756      269157.658
#Sta/Elev= 30
       0  769.33    19.5  759.88    29.3  754.45    78.1  724.19    97.7  711.51
     127   691.9   136.7   685.8   146.5  682.18   156.3  681.02     166   680.8
   214.9  681.39   233.7  681.26   242.7  680.81   251.8  679.75   265.4  677.39
   269.9  676.75   278.9  676.29   280.4  676.47     288  677.41   315.4  683.66
   324.6  687.04   333.8  692.06     343  697.72   352.2   701.1   361.4  703.67
   370.6  707.51   379.8  713.04   416.6  736.86   425.8  742.59     435  747.87
#Mann= 3 , 0 , 0
       0      .1       0   265.4    .045       0   280.4      .1       0
Bank Sta=265.4,280.4
XS Rating Curve= 0 ,0
Exp/Cntr=0.3,0.1

Type RM Length L Ch R = 1 ,857.3   ,374.9,383.1,388.3
XS GIS Cut Line= 4
     1509351.891      269110.783     1509146.162      269048.283
     1509071.943      269020.939     1508946.943      268974.064
#Sta/Elev= 30
       0  754.83    19.6  740.83    29.3  734.29    39.1  728.06    48.9  722.17
    58.6   716.6    97.7  694.62   107.5  689.66   117.3  685.64     127  683.23
   136.8  682.41   223.8  680.08   232.6  678.84   250.2  674.72   251.4  674.63
     259  674.07   266.4  675.46   267.7   675.7   285.3  680.91   294.1  684.38
   303.6  690.36   313.2  698.06   322.7  705.96   332.2  712.21   341.8  715.36
   351.3  718.66   360.9  723.97   389.5  743.11   408.5  756.22   427.6  768.56
#Mann= 3 , 0 , 0
       0      .1       0   251.4    .045       0   266.4      .1       0
Bank Sta=251.4,266.4
XS Rating Curve= 0 ,0
Exp/Cntr=0.3,0.1

Type RM Length L Ch R = 1 ,474.1   ,148.1,163.9,172
XS GIS Cut Line= 4
     1509497.724      268912.866      1509332.36      268742.293
     1509246.422      268677.189     1508983.401      268567.814
#Sta/Elev= 30
       0  702.63      19  695.22    28.5  692.19      38  689.96    85.5  684.29
   104.5  682.59   142.5  679.98   218.6  678.66   247.4  677.73   257.2  676.31
     267  673.76   271.2  672.99   276.8  671.97   286.2     673   296.4  676.67
   306.2  679.48     316  680.27   414.1  682.11   453.4  681.99   492.7  680.25
   502.6  680.36   512.4  681.36   522.2  683.58   541.8  689.15   561.5  693.44
   581.1  698.68   600.8   701.8   610.6  704.15   620.4  707.89   630.2  712.79
#Mann= 3 , 0 , 0
       0      .1       0   271.2    .045       0   286.2      .1       0
#XS Ineff= 2 , 0
                          394.48          682.04
Permanent Ineff=
       F       F
Bank Sta=271.2,286.2
XS Rating Curve= 0 ,0
Exp/Cntr=0.3,0.1

Type RM Length L Ch R = 1 ,310.2   ,73.7,67,65.8
XS GIS Cut Line= 5
     1509543.297       268908.96     1509406.579       268627.71
     1509354.495      268545.679     1509285.485      268411.564
     1509013.349      268270.939
#Sta/Elev= 30
       0  695.93    19.5  691.63    29.3   689.9    68.4  684.07    78.2  683.02
      88  682.67   136.8  683.08   166.1  682.56   244.3  682.57   312.7  682.11
   322.4  680.98   332.2  679.15   341.9  676.48   351.2  674.47   361.3  672.32
   366.2  672.91     371  673.48   390.4  677.69   409.9   679.5   466.4  682.89
   494.7  683.74     523  684.02   560.7  685.25   579.9  682.57     599   681.5
   656.4  681.54   761.7  680.93   790.5  681.35   838.3  683.61     867  684.59
#Mann= 3 , 0 , 0
       0      .1       0   351.2    .045       0   366.2      .1       0
Bank Sta=351.2,366.2
XS Rating Curve= 0 ,0
Exp/Cntr=0.3,0.1

Type RM Length L Ch R = 1 ,243.2   ,78.4,80.2,81.6
XS GIS Cut Line= 5
     1509592.776      268867.293     1509456.058      268586.043
     1509403.974      268504.012     1509334.964      268369.897
     1509062.829      268229.272
#Sta/Elev= 30
       0  687.88     9.8  687.37    29.3   687.3    97.7  689.85     127  690.02
   166.1  689.07   244.3  685.78   341.9  683.51   351.6  680.59   361.3  674.18
     371  671.77   373.5   672.2   380.7  673.42   390.4  677.64   400.2  680.71
   409.9  682.59   419.3  683.72   438.2  684.93   560.7     685   589.4  686.42
   627.7  689.11   656.4  689.47   675.6  689.01   685.2  688.23   704.3  686.12
   723.4  683.38   742.6  681.75   752.2  681.52   780.9  682.71     867  684.09
#Mann= 3 , 0 , 0
       0      .1       0   361.3    .045       0   373.5      .1       0
Bank Sta=361.3,373.5
XS Rating Curve= 0 ,0
Exp/Cntr=0.3,0.1

Type RM Length L Ch R = 1 ,163     ,164.6,163,160.3
XS GIS Cut Line= 5
     1509612.308      268836.043      1509519.86      268544.376
     1509474.287      268459.741     1509405.276      268325.626
     1509133.141      268185.001
#Sta/Elev= 30
       0  690.49    19.1  690.76    38.2  690.01      86  685.94   172.1  680.94
   181.7  680.22   191.2  679.19   229.5  674.68   267.7  671.77   277.3  671.43
     306  672.13   325.2  673.82   334.8  673.65   351.9  670.87     354   670.5
   363.6  670.12   366.9  670.24   373.3  670.48   392.5  673.94   402.1  675.25
   411.5  676.21   449.2  678.24   477.5  679.14   534.1  680.31   552.9  680.46
   658.2  683.46   734.8  686.16   830.5  689.89   849.7  690.43   859.2  690.45
#Mann= 3 , 0 , 0
       0      .1       0   351.9    .045       0   366.9      .1       0
Bank Sta=351.9,366.9
XS Rating Curve= 0 ,0
Exp/Cntr=0.3,0.1

Chan Stop Cuts=-1
Use User Specified Reach Order=0
Composite Channel Slope=5